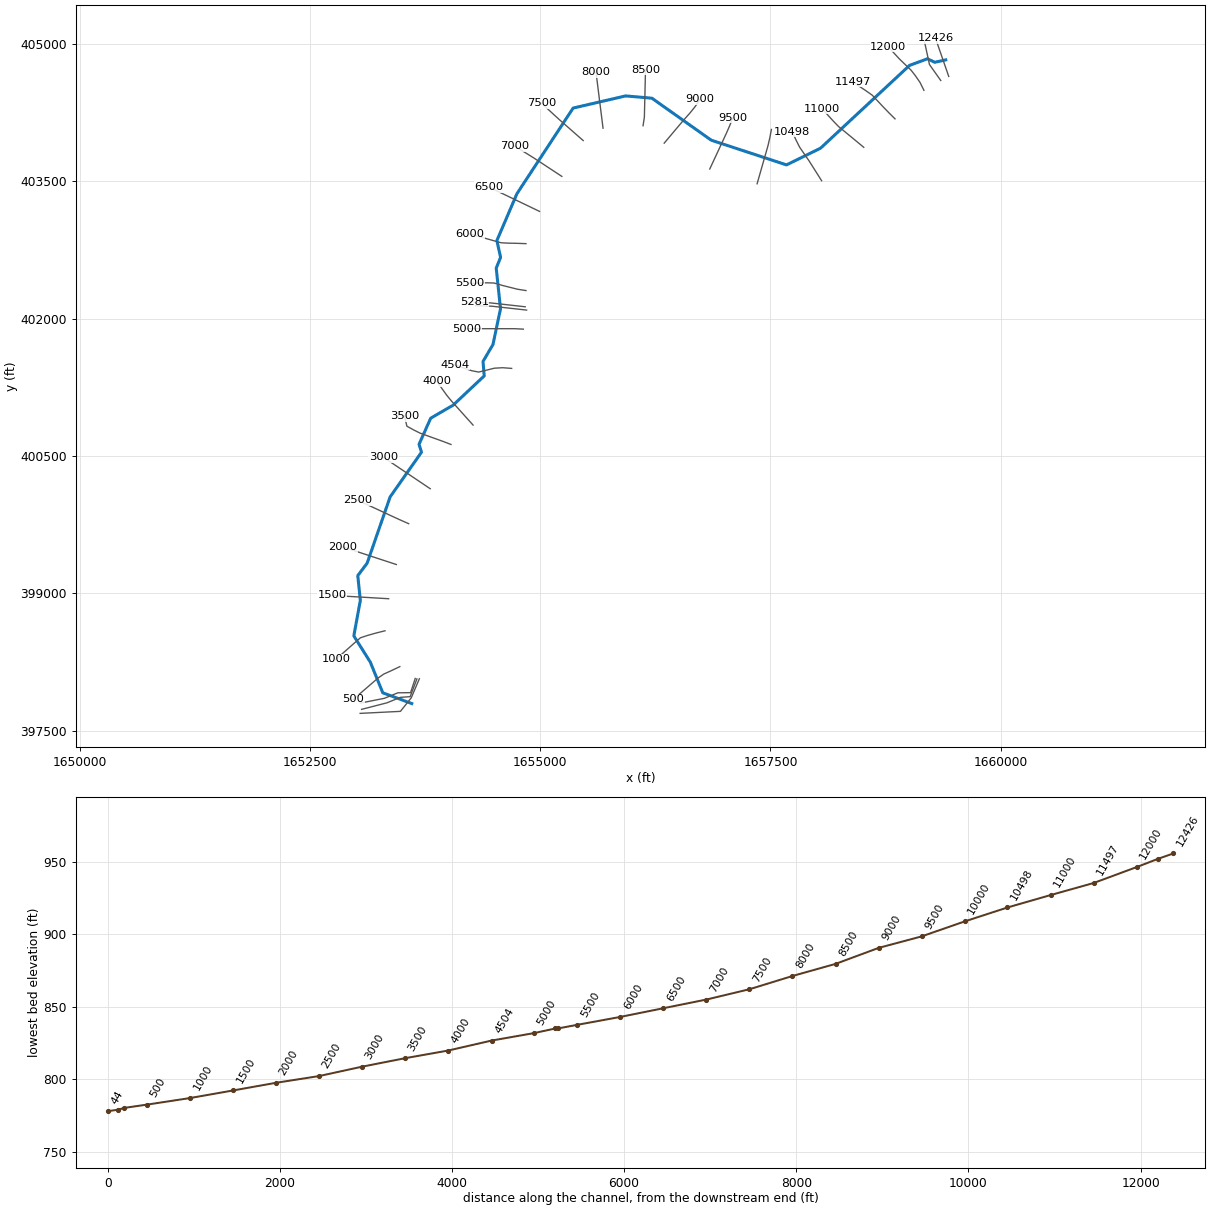
--- FOURMLRN.prj (project) ---

Proj Title=FOURMLRN
Current Plan=p01
Default Exp/Contr=0,0
English Units
Geom File=g01
Flow File=f01
Plan File=p01
BEGIN DESCRIPTION:
---------- MODELED AS PART OF WVEMD CTP PROGRAM, 2023----------
Stream Name: Fourmile Run
Flood Zone:  AFH
Wetzel County, WV
HEC-RAS Version: RAS 6.3
Vertical Datum: NAVD88
Projection: NAD 1983 StatePlane West Virginia S FIPS 4702 (US Feet)
Terrain: 1-meter West Virginia FEMA R3 South Central (collected 2018-2020)
Land Use: 2019 NLCD
Hydrologic Method:
WV 2010 Regional Regression Equations
Additional Model Notes:
None
END DESCRIPTION:
DSS Export Rating Curves= 0
DSS Export Rating Curve Sorted= 0
DSS Export Volume Flow Curves= 0
DXF OffsetX= 0
DXF OffsetY= 0
DXF ScaleX= 0
DXF ScaleY= 0

--- FOURMLRN.p01 (plan) ---

Plan Title=Floodplain
Program Version=4.00
Geom File=g01
Flow File=f01
K Sum by GR=0
Std Step Tol=0.01
Critical Tol=0.01
Num of Std Step Trials=20
Max Error Tol=0.3
Flow Tol Ratio=0.001
Split Flow NTrial=30
Split Flow Tol=0.02
Split Flow Ratio=0.02
Log Output Level=0
Friction Slope Method=1
Unsteady Friction Slope Method=2
Unsteady Bridges Friction Slope Method=1
Global Log Level=0
CheckData=False
Run HTab=0
Run UNet=0
Run PostProcess=0
UNET Theta=0
UNET Theta Warmup=0
UNET ZTol=0
UNET ZSATol=0
UNET MxIter=0
UNET MaxInSteps=0
UNET DtIC=0
UNET DtMin=0
UNET MaxCRTS=0
UNET WFStab=0
UNET SFStab=0
UNET WFX=0
UNET SFX=0
UNET DSS MLevel=0
UNET DZMax Abort=0
UNET Convert EG Bridges=0
UNET Use Existing IB Tables=0
UNET Froude Limit=0
UNET Froude Power=0
Write IC File=0
Echo Input=False
Echo Output=False
Write Detailed=0

--- FOURMLRN.f01 (steady flow) ---

Flow Title=Flow
Program Version=6.31
Number of Profiles= 1
Profile Names=F01pct
River Rch & RM=FOURMLRN,Main            ,12426
     678
River Rch & RM=FOURMLRN,Main            ,8500
     789
River Rch & RM=FOURMLRN,Main            ,7500
    1110
River Rch & RM=FOURMLRN,Main            ,3500
    1360
Boundary for River Rch & Prof#=FOURMLRN,Main            , 1
Up Type= 0
Dn Type= 3
Dn Slope=0.00859
DSS Import GetInterval= 0
DSS Import GetPeak= 0
DSS Import FillOption= 0

--- FOURMLRN.g01 (geometry) ---

Geom Title=Geometry
Program Version=6.31

River Reach=FOURMLRN        ,Main
Reach XY= 30
     1659404.453      404823.126     1659284.921      404796.912
     1659206.282      404835.358     1659011.256       404763.01
     1658043.468      403858.832     1657674.737      403677.088
     1656857.237      403946.559     1656212.395      404404.764
     1655927.196      404429.929       1655356.1      404297.116
     1654745.509      403362.181     1654527.765       402851.55
     1654568.308      402667.708     1654520.775      402550.623
      1654567.38      402105.996      1654485.01      401715.258
     1654377.375      401532.521     1654390.527      401374.357
     1654052.049      401054.568     1653809.092      400913.016
     1653682.422      400628.528     1653708.725      400541.313
     1653368.198      400053.946     1653118.347      399330.308
     1653016.679      399194.972     1653044.588      398924.743
     1652973.708       398537.12     1653152.901      398250.722
     1653288.237      397916.258     1653602.964      397798.603

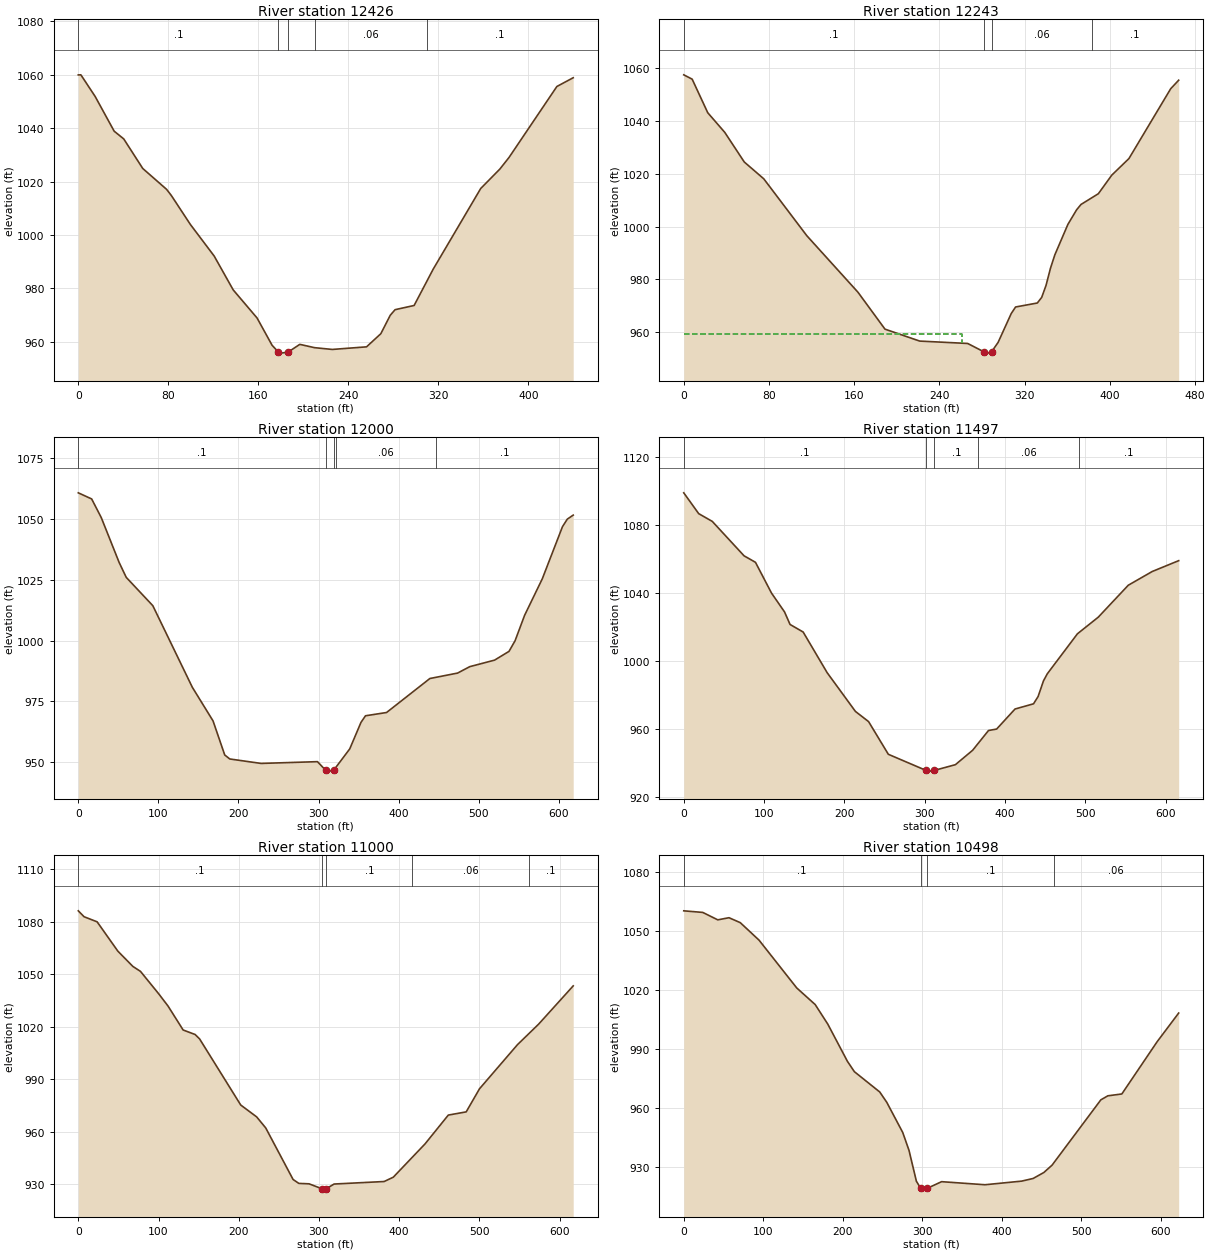
Type RM Length L Ch R = 1 ,12426   ,183.1,183.1,183.1
XS GIS Cut Line= 2
1659437.00296935404642.3720642381659293.47332597405058.240005306
#Sta/Elev= 30
       0 1059.91     2.3 1059.94      15 1051.84    31.9 1038.85    40.4 1035.96
    57.3  1024.9    78.5 1017.08    82.7 1014.79    99.6 1003.96   120.8  992.12
   137.7  979.46   158.9  968.95   172.3  958.72  177.93956.1776     180   955.8
  186.44956.1683   196.9  959.08     210  957.84   225.8  957.18   256.2  958.15
   268.9  963.06   277.3  969.98   281.6  972.06   298.5  973.63   315.4  987.18
   357.7 1017.41   374.7 1024.67   382.8 1028.99   425.4 1055.58   439.9 1058.85
#Mann= 5 ,-1,0
       0      .1       0  177.93    .045       0  186.44      .1       0
     210     .06       0     310      .1       0
Bank Sta=177.93,186.44
XS Rating Curve= 0 ,0
Exp/Cntr(USF)=0,0
Exp/Cntr=0.3,0.1

Type RM Length L Ch R = 1 ,12243   ,242.7,242.7,242.7
XS GIS Cut Line= 3
1659350.28808017404598.118558181 1659227.6921248404772.153375951
1659174.53863365405018.202601073
#Sta/Elev= 30
       0 1057.59     7.9 1055.94    22.5 1043.22    38.5 1035.75    56.8 1024.51
    75.1 1018.13   115.5  996.54   163.5   975.1   188.9  961.07   221.5  956.54
   266.5  955.64  281.71  952.48   286.9  951.97  288.98  952.47   295.1  956.05
   307.4  966.98   311.5  969.48   331.9  970.99     336  973.12   340.1   977.7
   344.2  984.12   348.3  989.23   360.6 1000.83   368.8 1006.37   372.9 1008.39
   389.2 1012.47   401.8 1019.52   417.9 1025.81   457.1 1052.31   464.6 1055.55
#Mann= 4 ,-1,0
       0      .1       0  281.71    .045       0  288.98     .06       0
  382.88      .1       0
#XS Ineff= 2 , 0
          260.96  959.17
Permanent Ineff=
       F       F
Bank Sta=281.71,288.98
XS Rating Curve= 0 ,0
Exp/Cntr(USF)=0,0
Exp/Cntr=0.3,0.1

Type RM Length L Ch R = 1 ,12000   ,502.4,502.4,502.4
XS GIS Cut Line= 6
1659167.49780583404490.8163164261659124.72787826404577.592389584
1659074.25849101404650.7874531751659027.79696976404710.703343838
1658901.90319267404832.258875012 1658779.2771256404966.123436674
#Sta/Elev= 30
       0 1060.68    16.7 1058.17    28.7 1050.51      51  1032.1    59.9 1025.96
    93.1 1014.33   142.4  980.85   168.3  967.02   182.9  953.03   189.2  951.39
   228.3  949.56   298.7  950.29  308.74946.8346   313.5   946.4   319.1  946.82
     339  955.52   353.1  966.44   358.7  969.13     385  970.47   439.1  984.43
   473.7  986.66   488.9   989.3   519.9  991.98   537.9  995.57   545.5  999.94
   557.4 1010.38   579.5 1025.38   604.7 1046.78   610.7 1049.87   618.1 1051.53
#Mann= 5 ,-1,0
       0      .1       0  308.74    .045       0   319.1      .1       0
  321.47     .06       0  446.47      .1       0
Bank Sta=308.74,319.1
XS Rating Curve= 0 ,0
Exp/Cntr(USF)=0,0
Exp/Cntr=0.3,0.1

Type RM Length L Ch R = 1 ,11497   ,497.6,497.6,497.6
XS GIS Cut Line= 6
1658853.29863109404179.4612960821658786.79613942404245.805979669
1658726.03116909404308.9994228331658606.54978076404437.159599587
1658544.78218776404481.1982254241658392.76247868404584.431286678
#Sta/Elev= 30
       0 1098.71    18.6 1086.49    35.5 1081.95    75.1 1061.74    89.3 1057.93
   109.3 1039.86   125.5 1028.82   132.4 1021.44   148.7 1017.01   178.6  993.14
   213.8  970.41   230.2  964.42   254.8  945.24   301.7  935.79   307.2  935.36
  312.05935.7816   338.3  939.14   359.8   947.6   379.5  959.18   389.7  960.07
   412.6  971.82   435.6  974.87   441.3  979.13     448  988.33   452.8  992.51
   490.3 1015.97   516.2  1025.7   553.6 1044.46   583.4 1052.52   616.4 1058.89
#Mann= 5 ,-1,0
       0      .1       0   301.7    .045       0  312.05      .1       0
  366.82     .06       0  492.68      .1       0
Bank Sta=301.7,312.05
XS Rating Curve= 0 ,0
Exp/Cntr(USF)=0,0
Exp/Cntr=0.3,0.1

Type RM Length L Ch R = 1 ,11000   ,502.1,502.1,502.1
XS GIS Cut Line= 6
1658513.66151509403868.9665102511658441.64952001403928.977217004
1658239.41895334404096.3364623341658186.74583034404150.906235084
1658126.62619993404217.0409453361658063.30841318404288.526366666
#Sta/Elev= 30
       0 1086.14     7.2 1082.77    23.5 1079.85    49.3 1063.11    68.1 1054.35
    77.5 1051.56   100.2 1038.75   111.9 1031.72   130.7 1018.04   145.7 1015.45
   151.3  1012.9   202.5  975.17   222.4  968.36   233.7  962.05   267.8  932.59
     275  930.36   287.7  930.12   303.4  927.37   307.6  927.09  309.36927.3642
   318.9     930   381.3  931.44   392.7  933.91   432.3  952.94   461.3  969.41
   483.6  971.24   500.2  984.45   547.5 1009.64   573.9 1021.38     617 1043.24
#Mann= 5 ,-1,0
       0      .1       0   303.4    .045       0  309.36      .1       0
  416.24     .06       0  561.46      .1       0
Bank Sta=303.4,309.36
XS Rating Curve= 0 ,0
Exp/Cntr(USF)=0,0
Exp/Cntr=0.3,0.1

Type RM Length L Ch R = 1 ,10498   ,497.9,497.9,497.9
XS GIS Cut Line= 6
1658055.85370368403504.3435518441657919.48127301403721.192855671
1657861.56505026403805.2865195131657817.98967808403868.869397596
 1657777.1334606403949.6976480041657737.62074435404037.800162092
#Sta/Elev= 30
       0 1060.09    23.9 1059.28    42.8  1055.5    56.9 1056.59    71.1 1054.07
    94.7 1045.17   142.1 1020.86   165.3 1012.41   181.2 1002.43   205.9  983.49
   214.6  978.26   246.5  967.93   255.4  962.64   275.4  947.35   283.3  938.25
   292.6  922.53  297.93918.9786   301.3  918.51  306.47918.9681   324.3   922.3
   378.9  920.74     425  922.58   439.5  923.94   452.9  926.97   463.3  930.73
   524.6  963.93   533.4  965.98     551  966.92   595.4   993.5   622.5 1008.09
#Mann= 4 ,-1,0
       0      .1       0  297.93    .045       0  306.47      .1       0
  465.36     .06       0
Bank Sta=297.93,306.47
XS Rating Curve= 0 ,0
Exp/Cntr(USF)=0,0
Exp/Cntr=0.3,0.1

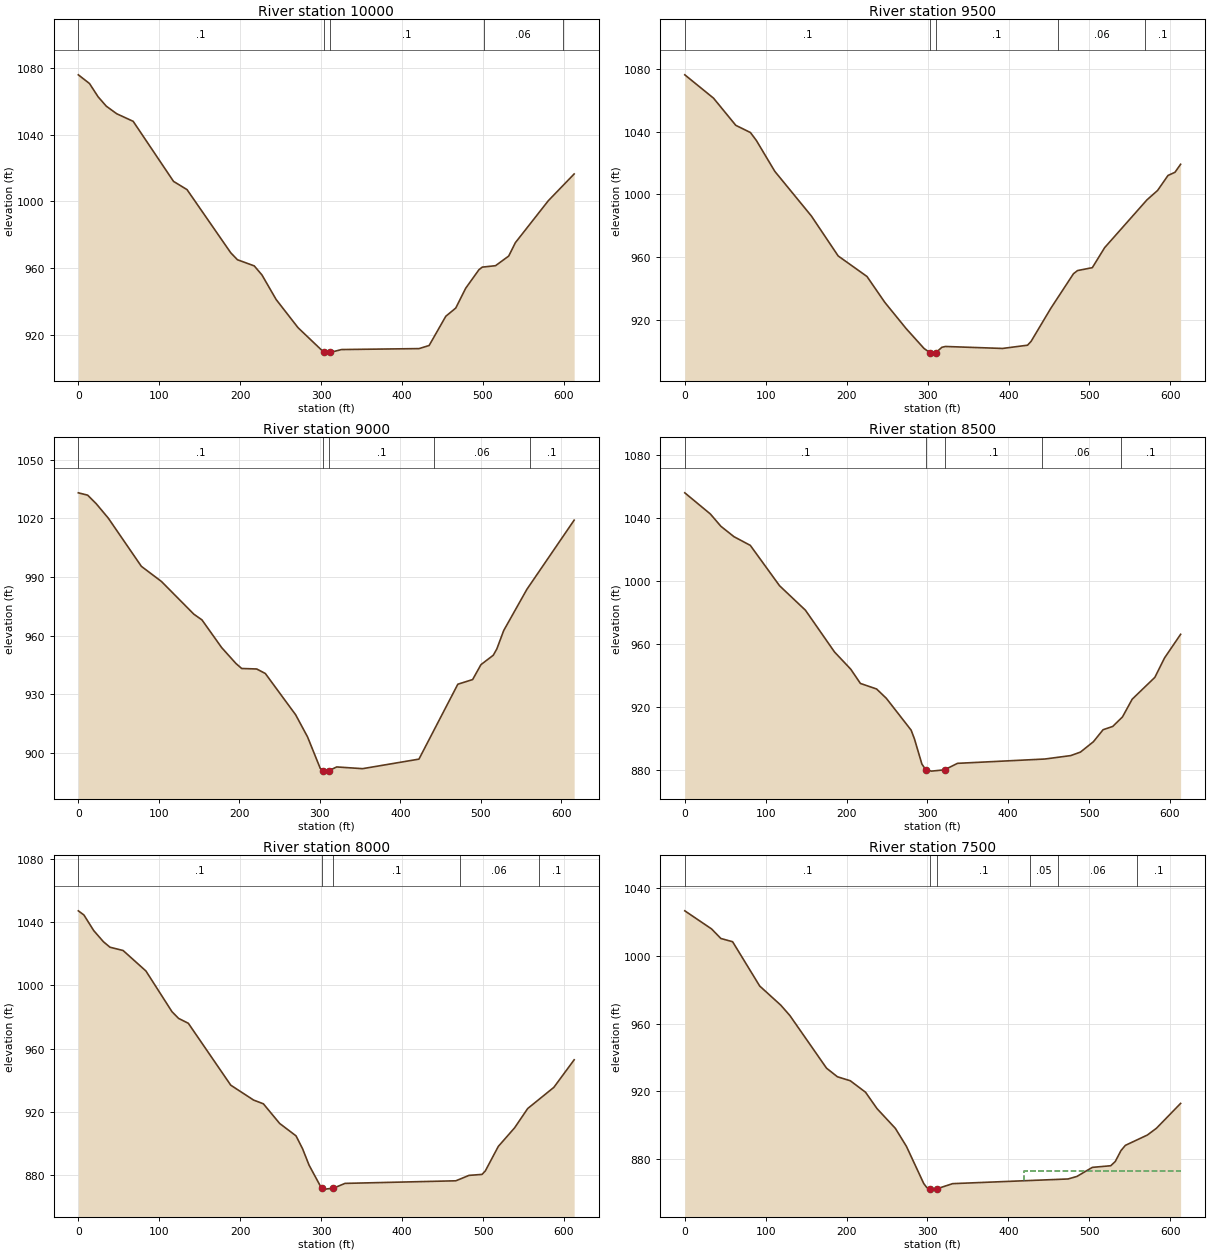
Type RM Length L Ch R = 1 ,10000   ,500,500,500
XS GIS Cut Line= 6
1657355.15563001 403471.303263591657380.78451575403561.481889009
1657404.70507158403645.6487154221657473.05007926403886.125268593
 1657492.7793705403971.4833655951657510.47290467404063.917563915
#Sta/Elev= 30
       0 1076.05    13.8 1070.83    24.4 1062.89    34.5 1057.25    47.4 1052.68
    67.8 1048.12   117.7 1012.04   134.4 1007.09   188.4  969.18   196.7  964.98
   217.5  961.28     227  955.85   244.6  941.06   271.6  924.18  303.68909.3404
     309  908.88  311.71909.3369   325.4  911.03   421.3   911.6   433.7  913.47
   454.3  931.01   466.6  935.95   478.9  947.86   495.3  958.99   499.4  960.54
   515.8   961.4   532.1   967.2   540.3  975.21     581  1000.4     613  1016.5
#Mann= 5 ,-1,0
       0      .1       0  303.68    .045       0  311.71      .1       0
  501.25     .06       0  598.86      .1       0
Bank Sta=303.68,311.71
XS Rating Curve= 0 ,0
Exp/Cntr(USF)=0,0
Exp/Cntr=0.3,0.1

Type RM Length L Ch R = 1 ,9500    ,499.5,499.5,499.5
XS GIS Cut Line= 6
1656840.68979542403632.3170491761656880.10703942403717.377902672
1656916.89797634403796.7675076721657022.01718867 404023.59316951
1657056.84225026404103.8935338411657091.62630142404191.081351593
#Sta/Elev= 30
       0 1076.46    35.5 1061.54      63 1044.18    81.1 1039.57    88.4 1034.52
   111.2 1014.77   156.4  986.21   189.5  960.68   225.1  947.55   247.1  931.03
   273.6  914.18   295.6  901.53   303.1   898.8   308.8  898.56  310.04898.8012
   317.7  902.31   322.1  902.81   392.6  901.55   423.5  903.63   427.9  906.12
   452.1  927.12   480.2  949.32   485.3  951.35   503.5  953.19   518.7  965.96
     571  996.53   584.1 1002.52     597 1012.13   605.6 1014.15   612.6 1019.29
#Mann= 5 ,-1,0
       0      .1       0   303.1    .045       0  310.04      .1       0
  461.25     .06       0  568.78      .1       0
Bank Sta=303.1,310.04
XS Rating Curve= 0 ,0
Exp/Cntr(USF)=0,0
Exp/Cntr=0.3,0.1

Type RM Length L Ch R = 1 ,9000    ,500.5,500.5,500.5
XS GIS Cut Line= 6
1656345.80659884403914.4985714261656510.32529867 404110.87777184
1656575.34747835404186.8913993391656625.77683942404243.380131513
1656681.18486509404312.5384577511656734.56992893404391.506803751
#Sta/Elev= 30
       0 1033.03    11.6 1031.83    22.3 1027.43    37.2 1020.09    78.3  995.42
   103.3  987.65   143.5  970.93   153.6     968     178  953.86   195.7  945.74
   202.9  943.15   221.6  942.89   232.3  940.58     270  919.43   284.7  908.17
   300.5  892.05  303.97890.8459   306.9  890.63     311  890.85     321  892.77
   353.1  891.89   423.1  896.77   471.4   935.1   489.8  937.48   500.1  945.11
   515.4  949.92   519.8   953.1   528.4  962.58   557.2  983.66   615.9 1019.05
#Mann= 5 ,-1,0
       0      .1       0  303.97    .045       0     311      .1       0
  441.94     .06       0  560.56      .1       0
Bank Sta=303.97,311
XS Rating Curve= 0 ,0
Exp/Cntr(USF)=0,0
Exp/Cntr=0.3,0.1

Type RM Length L Ch R = 1 ,8500    ,500,500,500
XS GIS Cut Line= 6
 1656116.0852735404104.4611180131656130.34607175404197.835603178
1656136.59441884404460.2612594221656138.38017642404535.240112096
1656140.46252134404622.7153308391656142.69414417404716.438896671
#Sta/Elev= 30
       0 1055.95    31.7  1042.5    44.6 1034.77    60.8 1028.16      81 1022.66
   117.2  997.07   149.2  981.57   185.2  955.07   205.2  944.22   217.2  935.16
   237.2  931.65   249.2  925.77   279.9  905.58     284  900.06   293.2  884.11
  298.05880.4226   305.2   879.6   321.2  880.43   337.2  884.53   445.3  887.27
   477.3  889.44   489.3  891.66   505.3  898.21   517.3  905.83   529.3  907.94
   541.3  913.96   553.3  925.19   581.3     939   593.3  951.32   613.2   966.3
#Mann= 5 ,-1,0
       0      .1       0  298.05    .045       0   321.2      .1       0
  441.96     .06       0  539.46      .1       0
Bank Sta=298.05,321.2
XS Rating Curve= 0 ,0
Exp/Cntr(USF)=0,0
Exp/Cntr=0.3,0.1

Type RM Length L Ch R = 1 ,8000    ,500,500,500
XS GIS Cut Line= 6
  1655681.257403404077.7088749261655669.62914543404170.734935582
1655658.77549259404257.5589089241655649.47268967404331.980019927
 1655637.0688431404431.2075117531655605.28412975404685.478656754
#Sta/Elev= 30
       0    1047     6.9 1044.37      19 1034.53    31.1 1027.43    39.1 1024.02
    55.3 1021.95    83.5 1009.01   115.7   983.3   123.8  979.09   135.9  975.98
   188.3   936.9   216.5   927.5   228.6  925.14   248.7  912.73   268.9  904.91
     277  896.78     285  886.44  300.44871.8235   304.5  871.26  315.09871.8328
   329.4  874.88   466.4  876.52   482.6  879.94   498.7  880.56   502.7   882.7
   518.8  898.23     539  910.02   555.1  922.15   587.4  935.52   612.5  952.92
#Mann= 5 ,-1,0
       0      .1       0  300.44    .045       0  315.09      .1       0
  471.25     .06       0  568.75      .1       0
Bank Sta=300.44,315.09
XS Rating Curve= 0 ,0
Exp/Cntr(USF)=0,0
Exp/Cntr=0.3,0.1

Type RM Length L Ch R = 1 ,7500    ,500,500,500
XS GIS Cut Line= 6
1655465.56492101403942.6405754981655273.41701134 404112.17895034
1655198.43159701404178.3389230071655143.20598568404229.107850343
1655079.00204584404288.7809593381655009.94969051404352.524598256
#Sta/Elev= 30
       0 1026.62    33.1 1015.92    44.6 1010.27    59.1 1008.36    92.6  982.17
   118.6  970.88   129.9  964.72   175.2  933.62   188.6  928.55   204.6  926.17
   223.4   919.4   237.6  909.72   260.3  898.03     274  887.37   295.3  865.49
   299.1  863.06   302.8  862.34     306  862.12  311.75 862.335   331.1  865.36
   473.7  868.12   484.6   869.6   503.8  874.98   526.5  875.94   532.1  878.44
   539.2  884.92   544.6  887.99   571.8   894.1   583.1  898.14   612.9   912.8
#Mann= 6 ,-1,0
       0      .1       0   302.8    .045       0  311.75      .1       0
  426.25     .05       0  461.27     .06       0  558.92      .1       0
#XS Ineff= 2 , 0
                          418.69          873.05
Permanent Ineff=
       F       F
Bank Sta=302.8,311.75
XS Rating Curve= 0 ,0
Exp/Cntr(USF)=0,0
Exp/Cntr=0.3,0.1

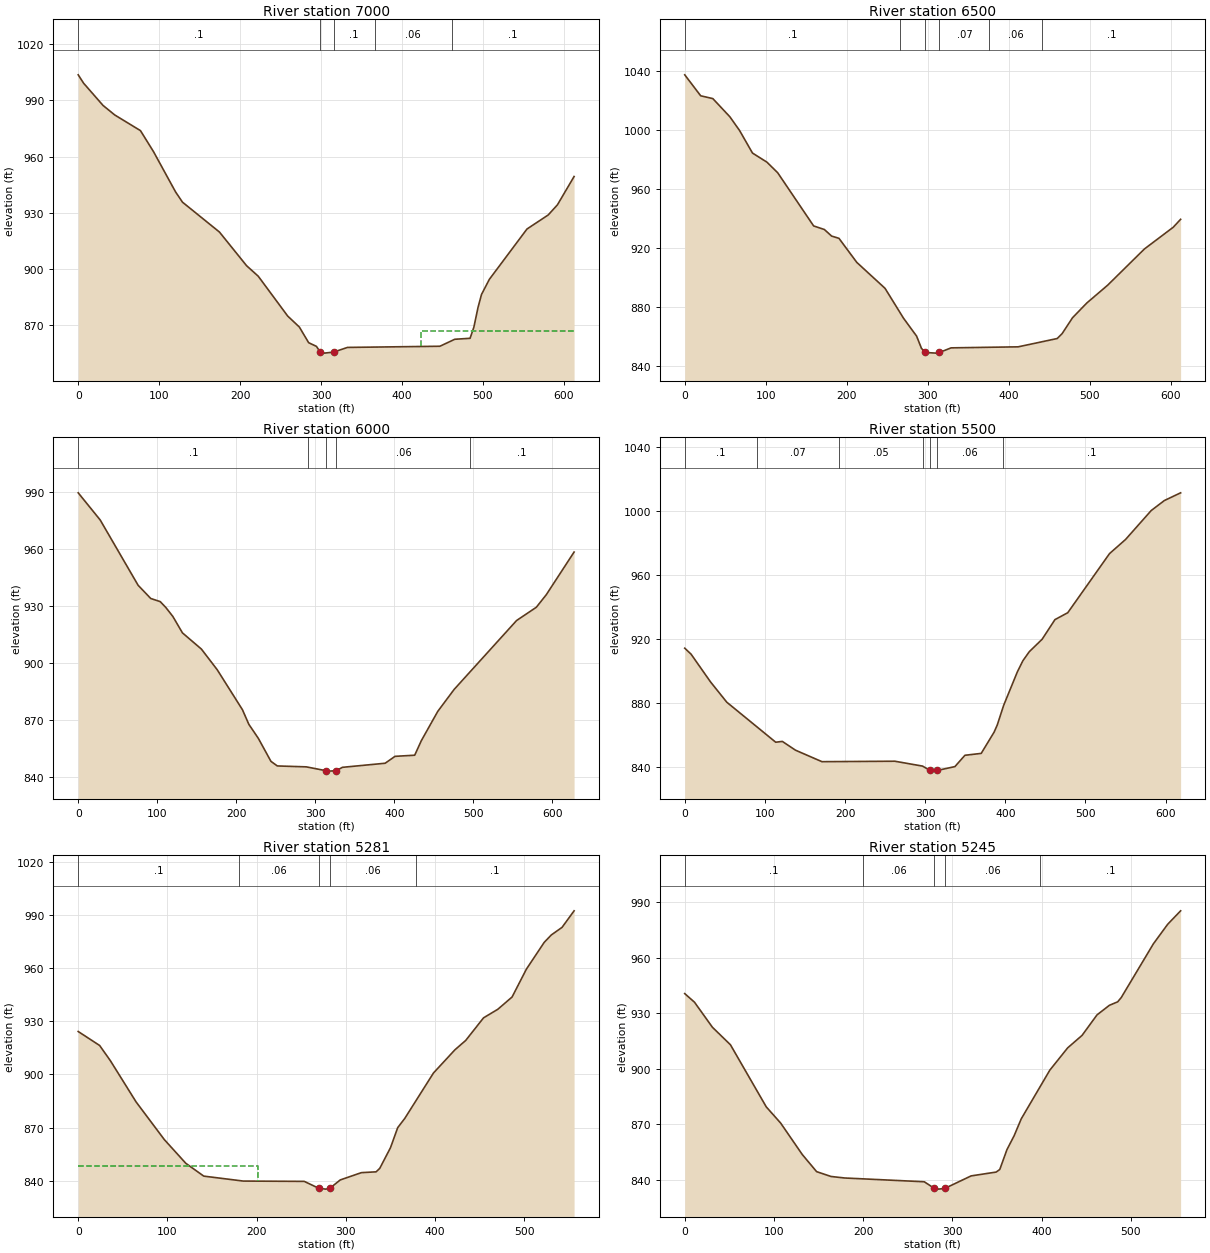
Type RM Length L Ch R = 1 ,7000    ,500,500,500
XS GIS Cut Line= 6
1655233.71728759403551.6242971721655155.48745717403603.288563922
1654936.44065118403747.9424740821654873.02837643403788.018509418
1654798.54394534403834.0125119241654718.52343608403882.965169922
#Sta/Elev= 30
       0 1003.67     6.7  999.18    30.7  987.31    45.2  982.21    76.9  973.87
      93  962.66   120.2  941.19   128.8  935.66   174.5  919.69     208  901.72
   222.4  896.11   258.8  874.82   273.2  868.96   284.7  860.59   294.3  858.64
  298.98855.5449   303.9  855.02  315.41855.5568   332.7  858.07   446.8  858.69
   465.2  862.42   484.1  862.94   488.8  868.89   493.9  879.39   498.2  886.32
   507.9  894.42   554.4  921.31   580.6  928.81     592  934.22   612.6  949.36
#Mann= 5 ,-1,0
       0      .1       0  298.98    .045       0  315.41      .1       0
  366.25     .06       0  461.26      .1       0
#XS Ineff= 2 , 0
                          423.72          866.89
Permanent Ineff=
       F       F
Bank Sta=298.98,315.41
XS Rating Curve= 0 ,0
Exp/Cntr(USF)=0,0
Exp/Cntr=0.3,0.1

Type RM Length L Ch R = 1 ,6500    ,500,500,500
XS GIS Cut Line= 6
1654991.48975368403169.5584602511654907.05291468403210.295255423
1654828.24565759403248.3168329151654603.08108167403356.948505417
1654524.27349651403394.9697548451654439.83665751403435.707206175
#Sta/Elev= 30
       0 1037.27    19.7 1023.09    34.7 1021.19    55.7 1008.92    67.7  999.64
    83.7  984.35   101.5  978.21   114.8  971.05   159.2  935.07   172.5  932.63
   181.4  928.21   190.5  926.68   212.5  910.42   247.4  892.86   270.2  872.67
   286.4  860.52   292.4  852.27   296.9  849.47   310.3  849.03   314.6  849.47
     329  852.59   411.9  853.29   460.1  858.91   466.1  862.19     479  872.97
   496.7  882.97   522.4  894.99   567.8  919.49   603.3  934.14   612.5  939.54
#Mann= 6 ,-1,0
       0      .1       0  266.25     .07       0   296.9    .045       0
   314.6     .07       0  376.25     .06       0  441.25      .1       0
Bank Sta=296.9,314.6
XS Rating Curve= 0 ,0
Exp/Cntr(USF)=0,0
Exp/Cntr=0.3,0.1

Type RM Length L Ch R = 1 ,6000    ,500,500,500
XS GIS Cut Line= 6
1654843.89326409402817.5476813321654743.63362209402821.208107084
1654650.44975334402823.1014759991654572.87313683 402827.34589009
1654476.66663635402854.6289720091654230.13792992402924.540249512
#Sta/Elev= 30
       0  989.79    27.8  975.49    75.8  941.04    91.8  934.07   103.8  932.42
     111  929.27   119.8  924.57   131.9  915.94   155.9  907.39   175.9   896.5
   207.9  875.36   215.9  867.73   227.9  860.35   243.9  848.18     252  845.76
   288.6  845.28   313.6  843.26   317.7  843.03  326.71843.2686   334.3  845.03
   388.4  847.19   400.9  850.83   425.8  851.42   434.2   859.1     455  874.54
   475.7  886.11   554.7  922.44   579.7  929.44   592.2  935.99   627.5  958.56
#Mann= 5 ,-1,0
       0      .1       0  291.22     .06       0   313.6    .045       0
  326.71     .06       0  496.22      .1       0
Bank Sta=313.6,326.71
XS Rating Curve= 0 ,0
Exp/Cntr(USF)=0,0
Exp/Cntr=0.3,0.1

Type RM Length L Ch R = 1 ,5500    ,218.4,218.4,218.4
XS GIS Cut Line= 6
1654843.91983885402305.6028390821654750.66608834402320.509961501
1654593.02729601402360.3445275131654496.96351175402388.124655679
 1654420.6677326402390.2644151751654235.44959909402384.102682084
#Sta/Elev= 30
       0  914.34     7.9  910.61    32.2  893.27    52.5   880.6   113.5  855.64
   121.8  856.14   138.2  850.66   171.2  843.49   262.2  843.77   296.7  840.73
  305.88838.0574     308  837.59  315.32838.0397   337.1  840.42   349.6  847.48
   369.9  848.66   385.9  861.84   389.9  866.35   397.9  878.64   415.1  899.66
   421.9   906.5   429.9  912.15   445.9  919.91   461.9  932.17   477.9  936.48
     530  973.38     550   982.2     582 1000.26   598.3 1006.47   618.7 1011.32
#Mann= 7 ,-1,0
       0      .1       0      90     .07       0  192.01     .05       0
  297.04     .06       0  305.88    .045       0  315.32     .06       0
  397.04      .1       0
Bank Sta=305.88,315.32
XS Rating Curve= 0 ,0
Exp/Cntr(USF)=0,0
Exp/Cntr=0.3,0.1

Type RM Length L Ch R = 1 ,5281    ,36.8,36.8,36.8
XS GIS Cut Line= 3
1654835.97533823402128.6566052171654459.77228436 402170.91129605
1654282.57519377402176.363514222
#Sta/Elev= 30
       0  924.31      24  916.41    36.1  907.76    64.9  884.46    96.5  863.19
   120.6  849.77   140.7  842.52     185  839.72   253.4  839.54   269.7835.6234
   277.6  835.16     282  835.62   293.7  840.36   317.4  844.48   333.9  844.94
     338  846.92     350  858.58   358.1  869.92   366.1  875.21   398.2  900.85
   422.2  913.94   434.3  919.24   454.3  932.03   470.3  936.87   486.3  943.82
   502.3  959.54   522.3  974.72   530.3  978.93   542.3   983.2   555.8  992.56
#Mann= 5 ,-1,0
       0      .1       0     180     .06       0   269.7    .045       0
     282     .06       0  378.57      .1       0
#XS Ineff= 2 , 0
          201.44  847.96
Permanent Ineff=
       F       F
Bank Sta=269.7,282
XS Rating Curve= 0 ,0
Exp/Cntr(USF)=0,0
Exp/Cntr=0.3,0.1

Type RM Length L Ch R = 1 ,5245    ,244.8,244.8,244.8
XS GIS Cut Line= 3
 1654850.9689382402092.5356598271654474.76588433 402134.79035066
1654297.56879374402140.242568832
#Sta/Elev= 30
       0  940.58    10.9  935.96      31  922.43    51.2  912.99    91.4  879.44
   107.5  870.72   131.7  853.77   147.8   844.5   163.9  841.89   179.2  841.07
   268.5  839.03   279.8  835.46   284.6  835.06   291.5 835.454     321   842.2
     349  844.26   353.1  845.66   361.1  856.33   369.2  863.88   377.2  873.02
   409.2  899.27   429.2   911.3   445.3  918.02   462.1   929.1     476  934.28
   485.3  936.16   489.3  938.49   525.3  967.47   541.3     978   555.8  985.26
#Mann= 5 ,-1,0
       0      .1       0     200     .06       0   279.8    .045       0
   291.5     .06       0  398.57      .1       0
Bank Sta=279.8,291.5
XS Rating Curve= 0 ,0
Exp/Cntr(USF)=0,0
Exp/Cntr=0.3,0.1

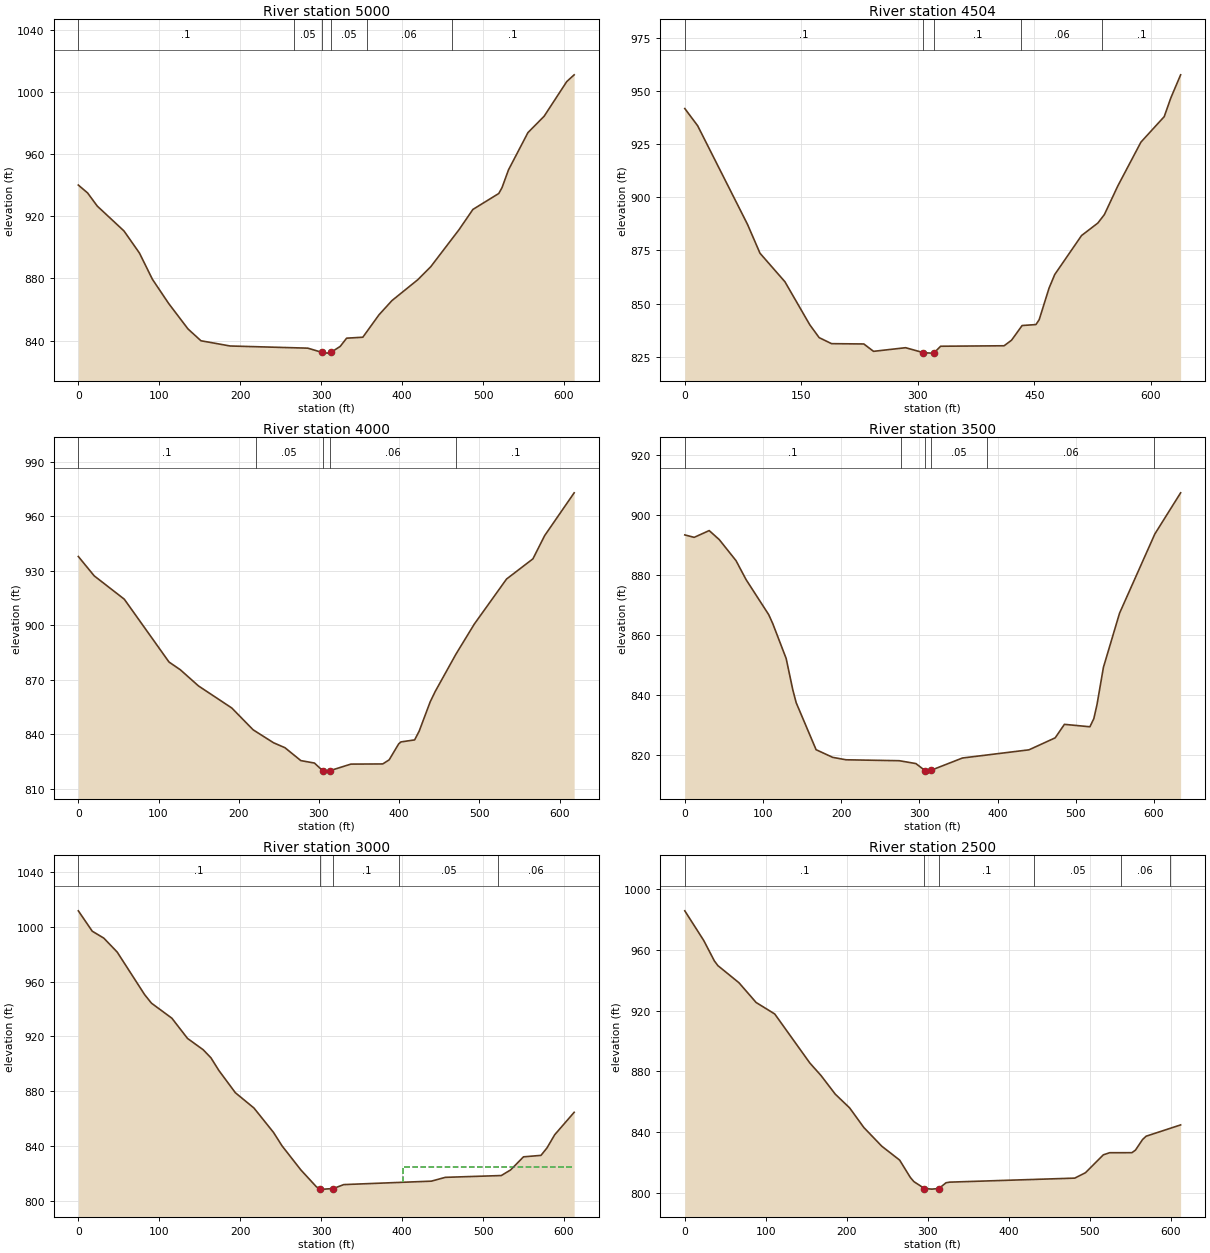
Type RM Length L Ch R = 1 ,5000    ,496.2,496.2,496.2
XS GIS Cut Line= 3
1654815.46615559401884.6535497611654721.73668426401889.564957261
 1654202.9867375401889.564957261
#Sta/Elev= 30
       0  940.14    11.4   935.1    23.4  926.61    56.4  910.59    75.5  896.37
    91.5   879.5   111.5  863.96   135.5  847.48   151.5  839.88   187.5  836.51
   283.5  835.11  300.69832.4556   307.5  831.91  312.13832.4347   323.5  836.21
   331.5  841.54   351.5  842.15   371.5  856.61   387.5  865.75   419.5  879.23
   435.5  887.61   470.5  911.51   487.5  924.45   519.5  934.73   523.5  938.52
   531.5  949.96   555.5  973.92   575.5  984.46   603.5 1006.82   612.6 1011.13
#Mann= 6 ,-1,0
       0      .1       0  266.36     .05       0  300.69    .045       0
  312.13     .05       0  356.36     .06       0  461.36      .1       0
Bank Sta=300.69,312.13
XS Rating Curve= 0 ,0
Exp/Cntr(USF)=0,0
Exp/Cntr=0.3,0.1

Type RM Length L Ch R = 1 ,4504    ,503.8,503.8,503.8
XS GIS Cut Line= 6
1654688.65374517401456.193120584 1654590.6749385401463.725913927
 1654500.9270865401458.4388509991654330.88969693401416.187951252
1654252.58440734401431.4005192521654068.34363408401495.700259417
#Sta/Elev= 30
       0  941.75    16.6  933.64    80.8  887.24    96.8  873.72   128.9   860.3
   160.9  840.07     173  834.01     189  831.17   230.5  831.03     243  827.56
   284.3  829.27  307.22826.9471   317.1  826.72   321.2  826.95   329.4  829.96
   411.1  830.18   420.7  832.79   434.3   839.7   452.1  840.15   456.3  842.46
   468.9  857.19   476.3  863.68   510.8  882.01   531.8  887.89   540.2  891.86
   557.4  905.25   587.3  925.96   617.3  937.96   625.8  946.76   638.4  957.61
#Mann= 5 ,-1,0
       0      .1       0  307.22    .045       0   321.2      .1       0
  433.43     .06       0  537.43      .1       0
Bank Sta=307.22,321.2
XS Rating Curve= 0 ,0
Exp/Cntr(USF)=0,0
Exp/Cntr=0.3,0.1

Type RM Length L Ch R = 1 ,4000    ,500.3,500.3,500.3
XS GIS Cut Line= 6
1654269.08437434 400837.792782591654098.41772093401028.939381927
1654031.81647618401103.5333928321653984.41630851401161.756045416
1653932.26254143401234.6525531711653877.45917334401314.968009338
#Sta/Elev= 30
       0   937.9    19.8  927.25    57.3  914.42   113.1  879.84     127  875.66
   149.9  866.68   191.4  854.55   217.9  842.59   243.4  835.45   257.6  832.74
   277.4  825.64   294.4  824.29  304.61820.1088   308.6  819.85   313.8  820.11
   339.8  823.71   379.5   823.8   387.5  826.03   399.4  834.82   402.2  835.91
   419.3  837.02     425  841.88   438.7  857.96     445  863.69   470.8  884.18
   493.7  900.73   533.9   925.5   566.8  936.61   581.4  949.37   618.2  972.92
#Mann= 5 ,-1,0
       0      .1       0  221.25     .05       0  304.61    .045       0
   313.8     .06       0  471.33      .1       0
Bank Sta=304.61,313.8
XS Rating Curve= 0 ,0
Exp/Cntr(USF)=0,0
Exp/Cntr=0.3,0.1

Type RM Length L Ch R = 1 ,3500    ,499.5,499.5,499.5
XS GIS Cut Line= 6
1654029.26694059400626.2272608431653941.73201068400659.867613509
1653694.89195317400749.1843640061653627.41702251400782.914283425
1653550.27380408400825.3774530891653524.48682614400936.701768132
#Sta/Elev= 30
       0  893.29      12  892.48    31.2  894.74    44.1  891.72    65.5  884.72
    78.4  878.38   107.3  866.72   112.5  863.72   129.6  852.12   138.1  841.68
   142.4  837.39   167.9  821.71   189.1  819.16   206.2  818.35   274.2  818.04
   295.5  817.09  307.08814.7781   311.1  814.57   314.2  814.78     355  818.94
   440.1  821.67   473.6  825.66   485.4  830.16     518  829.35     523  832.05
   527.1  836.77   535.3  849.17   555.9   867.2     601  893.59     634  907.32
#Mann= 6 ,-1,0
       0      .1       0  276.28     .05       0  307.08    .045       0
   314.2     .05       0  386.28     .06       0  599.77      .1       0
Bank Sta=307.08,314.2
XS Rating Curve= 0 ,0
Exp/Cntr(USF)=0,0
Exp/Cntr=0.3,0.1

Type RM Length L Ch R = 1 ,3000    ,500,500,500
XS GIS Cut Line= 6
1653803.91240442400142.9395135051653653.68304609400244.343182087
1653591.51978458400286.3040561681653508.63477975400342.251122758
1653446.47151826400384.2119968381653296.24183184400485.615665421
#Sta/Elev= 30
       0 1011.58    17.2  996.73    31.5  991.67      48  981.53    81.8  950.58
    90.3  944.29   115.6  933.29   134.9  918.56   154.2  910.34   163.8  904.46
   173.5  895.31     194  878.98   216.9  867.88   241.1  850.07   251.7  840.23
   274.8  822.79   294.1  810.42  297.92 809.171   303.8  808.73   315.1  809.17
   327.9  812.03   436.1  814.54   453.4  817.32   522.5  818.63     534  822.73
   549.9  832.27   571.5  833.33   578.9  838.73   588.5   848.4   612.5  864.72
#Mann= 5 ,-1,0
       0      .1       0  297.92    .045       0   315.1      .1       0
  396.25     .05       0  518.75     .06       0
#XS Ineff= 2 , 0
                          401.08          824.78
Permanent Ineff=
       F       F
Bank Sta=297.92,315.1
XS Rating Curve= 0 ,0
Exp/Cntr(USF)=0,0
Exp/Cntr=0.3,0.1

Type RM Length L Ch R = 1 ,2500    ,500,500,500
XS GIS Cut Line= 6
1653569.52639025399761.6154730021653483.82807083399799.667234167
1653404.32035585399836.2048907581653336.35559675399867.919066176
1653177.77192442399941.921214759 1653013.5268461400018.570011586
#Sta/Elev= 30
       0  985.86    23.4  966.29    36.6  952.76    40.9   949.7    66.9  938.42
    88.1  925.39   111.1  917.81   154.5  885.44   168.3  877.19   185.9  864.89
   203.6  855.86   221.2  842.89   243.3  830.59   265.4   821.4   278.6  809.97
     283  807.19   296.1802.6533   305.1  802.25   313.9  802.64   322.7  806.45
   327.2  806.86   481.7  809.51   494.9  813.05     517  824.87   524.8  826.27
   552.3  826.29   556.7  827.98   565.5  834.98   569.9  837.17   612.5  844.62
#Mann= 6 ,-1,0
       0      .1       0   296.1    .045       0   313.9      .1       0
  431.27     .05       0  538.77     .06       0  598.77      .1       0
Bank Sta=296.1,313.9
XS Rating Curve= 0 ,0
Exp/Cntr(USF)=0,0
Exp/Cntr=0.3,0.1

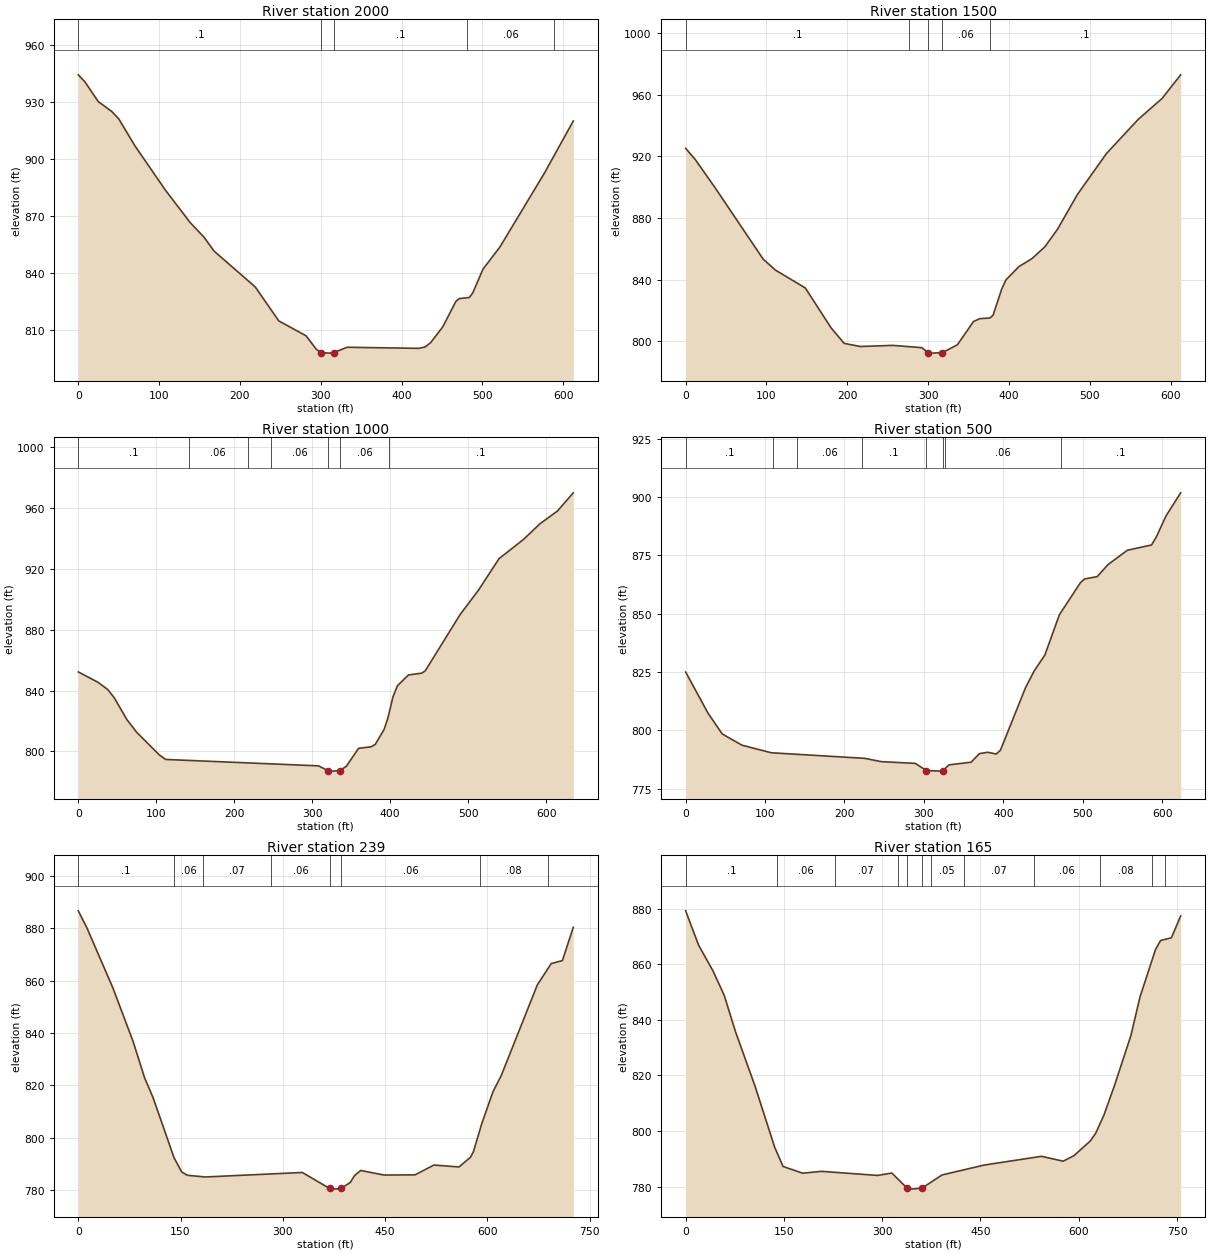
Type RM Length L Ch R = 1 ,2000    ,500,500,500
XS GIS Cut Line= 6
1653435.69627734399315.9608525041653346.66463126399345.328247845
1653192.34276143399396.2307050821653026.15050851 399451.04916501
1652943.05421801399478.4579028341652854.02257192399507.825298175
#Sta/Elev= 30
       0  944.43       8  940.84    24.8  930.27    41.3  925.15    50.1  921.18
    69.8  907.14   107.8  883.61   138.6  866.41   155.4  858.87     168  851.44
   218.9  832.55   248.1  814.62   281.8  806.76   294.4  799.71   300.1  797.89
   311.2  797.61  316.13 797.889   332.7  800.71   421.4  800.13   429.2  800.86
     436  803.15     451  811.47   467.1  824.83   471.3  826.36   483.9  826.98
   488.1  829.37   500.8  841.93   521.8  853.66   576.5  892.38   612.5  920.07
#Mann= 5 ,-1,0
       0      .1       0   300.1    .045       0  316.13      .1       0
  481.25     .06       0  588.75      .1       0
Bank Sta=300.1,316.13
XS Rating Curve= 0 ,0
Exp/Cntr(USF)=0,0
Exp/Cntr=0.3,0.1

Type RM Length L Ch R = 1 ,1500    ,500.2,500.2,500.2
XS GIS Cut Line= 6
1653351.83063142398942.6623865071653096.04013251 398957.79096517
1652996.21027967398963.6206779181652921.33411708398968.049474835
1652833.98291384398973.2158030871652740.39484642398978.750568926
#Sta/Elev= 30
       0  925.09    11.7  917.98    35.8  900.03    95.9  853.27   111.2  846.11
     148  834.59     180  808.67   196.1  798.65   216.1   796.6   256.2  797.33
   292.2  795.86  299.97 792.614   304.2  792.31  317.76792.6111   336.3  797.76
   356.3  812.88   364.3  814.69   376.4  815.08   380.4  816.89   391.2  834.04
   396.4  839.87   412.4  848.42   428.5  853.59   444.5  861.25   460.5  872.95
   484.6  895.06   520.6  921.67   559.8  943.78   589.6   957.5   612.5  972.76
#Mann= 5 ,-1,0
       0      .1       0  276.24     .06       0  299.97    .045       0
  317.76     .06       0  376.24      .1       0
Bank Sta=299.97,317.76
XS Rating Curve= 0 ,0
Exp/Cntr(USF)=0,0
Exp/Cntr=0.3,0.1

Type RM Length L Ch R = 1 ,1000    ,499.8,499.8,499.8
XS GIS Cut Line= 6
1653312.63287517398592.7214853321653214.17703535398567.973831415
1653121.76285009398541.8383850011653044.96247876398516.020195171
1652969.80088368398450.0583848361652777.97515184398280.155509427
#Sta/Elev= 30
       0  852.33    25.3   845.5    37.7  840.78    45.9   835.5    62.4  820.94
    74.8  812.68   103.7  797.84     112  794.76   308.1  790.54   320.2   787.4
   326.3  787.08  335.07787.3968   343.6  790.19   359.5  802.08   375.5  803.07
   380.9  804.69   392.2  814.54   396.9  821.71   403.5  835.82   409.2  843.18
   423.4  850.32   440.4   851.5     445  853.08   489.5  889.94   513.6  906.38
   539.5  926.78   570.7  939.35     592  949.73   614.3  958.06   634.8  970.11
#Mann= 7 ,-1,0
       0      .1       0  141.52     .06       0  217.56      .1       0
  247.56     .06       0   320.2    .045       0  335.07     .06       0
  398.58      .1       0
Bank Sta=320.2,335.07
XS Rating Curve= 0 ,0
Exp/Cntr(USF)=0,0
Exp/Cntr=0.3,0.1

Type RM Length L Ch R = 1 ,500     ,261.3,261.3,261.3
XS GIS Cut Line= 6
1653473.58366875398201.6569787561653382.90045117398158.339808166
1653300.00724426 398120.843820171653237.86432393398077.832423255
1653162.29557742398012.3391159181652968.64898309397844.514648423
#Sta/Elev= 30
       0  825.03    28.2  807.38      46   798.5    70.9  793.67   107.9  790.42
   225.4  788.03   246.2  786.62   289.1  785.87  303.14782.7988   322.3  782.55
     324   782.8   331.6  785.24   359.4  786.37   369.9  790.05   380.5  790.63
   391.1  789.88   396.4  791.53   427.8  818.21   438.8  825.46   452.3   832.3
   470.6   849.6     497  863.29   502.3  864.94   518.1  865.91   531.7  871.05
   556.1  877.23   586.6   879.5   592.5   882.8   604.9     892   623.3  901.86
#Mann= 8 ,-1,0
       0      .1       0   110.5     .05       0   140.5     .06       0
  221.48      .1       0  303.14    .045       0     324      .1       0
  327.05     .06       0  472.05      .1       0
Bank Sta=303.14,324
XS Rating Curve= 0 ,0
Exp/Cntr(USF)=0,0
Exp/Cntr=0.3,0.1

Type RM Length L Ch R = 1 ,239     ,73.6,73.6,73.6
XS GIS Cut Line= 5
1653640.87940503398072.8943566881653590.39590344397917.704333274
1653452.03371389397915.8345739561653306.19248706397856.002275772
1653044.42618251397803.649014862
#Sta/Elev= 30
       0  886.63      13  879.93    50.9  857.09    80.3  836.81    97.1  822.98
   109.7  815.26   140.5  792.29   151.8  786.85   160.2  785.59   186.3  784.95
   328.6  786.67   368.7  780.57   374.5  780.31   385.4 780.565   399.1  782.86
   405.3  785.51   414.4  787.44   448.5  785.69     494  785.76   521.7  789.51
   558.5  788.78   575.5  792.53   579.8  794.72   591.9   805.3   608.2   817.4
   620.4  823.63   673.4  858.32   693.8  866.47   710.2  867.62   726.2  880.33
#Mann= 8 ,-1,0
       0      .1       0     140     .06       0  183.19     .07       0
  283.19     .06       0   368.7    .045       0   385.4     .06       0
  589.21     .08       0  689.21      .1       0
Bank Sta=368.7,385.4
XS Rating Curve= 0 ,0
Exp/Cntr(USF)=0,0
Exp/Cntr=0.3,0.1

Type RM Length L Ch R = 1 ,165     ,121,121,121
XS GIS Cut Line= 5
1653659.08665383398067.6320873651653585.72150514397873.764989296
  1653479.145224397866.2859520231653333.30399718397806.453653839
 1653058.4493774397735.402799746
#Sta/Elev= 30
       0  879.21    19.7  866.89    41.8  857.56    58.9  848.77    76.1  835.71
     106  816.06   135.9  794.13   148.7  787.21   178.7  784.79   207.3  785.46
   293.1  783.99   314.7  784.85  337.95779.4261   343.3  779.06  360.74779.4122
   391.4  784.16   455.7  787.72   543.2  790.87   576.3  789.11   592.8  791.12
   617.6  796.36   625.9  799.18   638.5  805.71   654.8  816.51   679.6  834.27
   693.6  848.26   717.2  865.28     725  868.53   741.5  869.51   755.6  877.38
#Mann= 12 ,-1,0
       0      .1       0     140     .06       0  227.28     .07       0
  324.12     .06       0  337.95    .045       0  360.74     .06       0
  374.12     .05       0  424.12     .07       0  531.76     .06       0
  631.76     .08       0  711.76     .06       0  731.76     .08       0
Bank Sta=337.95,360.74
XS Rating Curve= 0 ,0
Exp/Cntr(USF)=0,0
Exp/Cntr=0.3,0.1

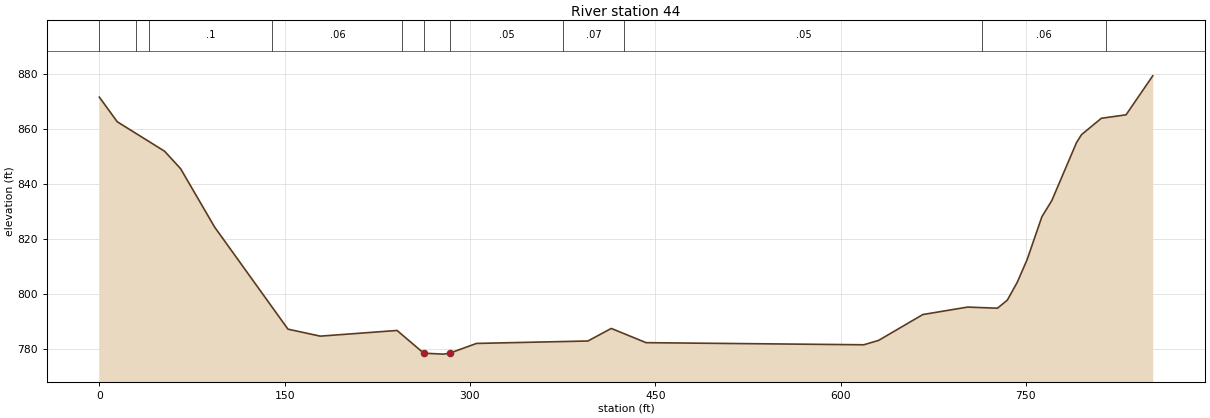
Type RM Length L Ch R = 1 ,44      ,,,
XS GIS Cut Line= 4
1653685.75362867398069.1548380521653597.87494071397861.611553727
1653479.83404333397713.4084469341653042.55642319397691.463455767
#Sta/Elev= 30
       0  871.73    14.5  862.75    52.8  852.01    65.8  845.63    93.3  824.35
   152.7  787.11   178.8  784.56     241  786.63   262.6  778.34   278.6     778
  283.56778.3365   305.3   781.9   395.5  782.79   414.4  787.37   442.6  782.18
   618.8  781.41   630.8  783.01   666.6  792.44   702.9  795.16     727  794.75
     735   797.7     743  804.18     751  812.46     763  828.14     771  834.01
     791  855.15     795  858.03   811.1  864.02   831.1  865.28   852.7   879.5
#Mann= 11 ,-1,0
       0      .1       0      30     .06       0      40      .1       0
     140     .06       0  245.38     .05       0   262.6    .045       0
  283.56     .05       0  375.38     .07       0  424.85     .05       0
  714.85     .06       0  814.85     .08       0
Bank Sta=262.6,283.56
XS Rating Curve= 0 ,0
Exp/Cntr(USF)=0,0
Exp/Cntr=0.3,0.1
LCMann Table=0

Chan Stop Cuts=-1
Use User Specified Reach Order=0
Composite Channel Slope=5